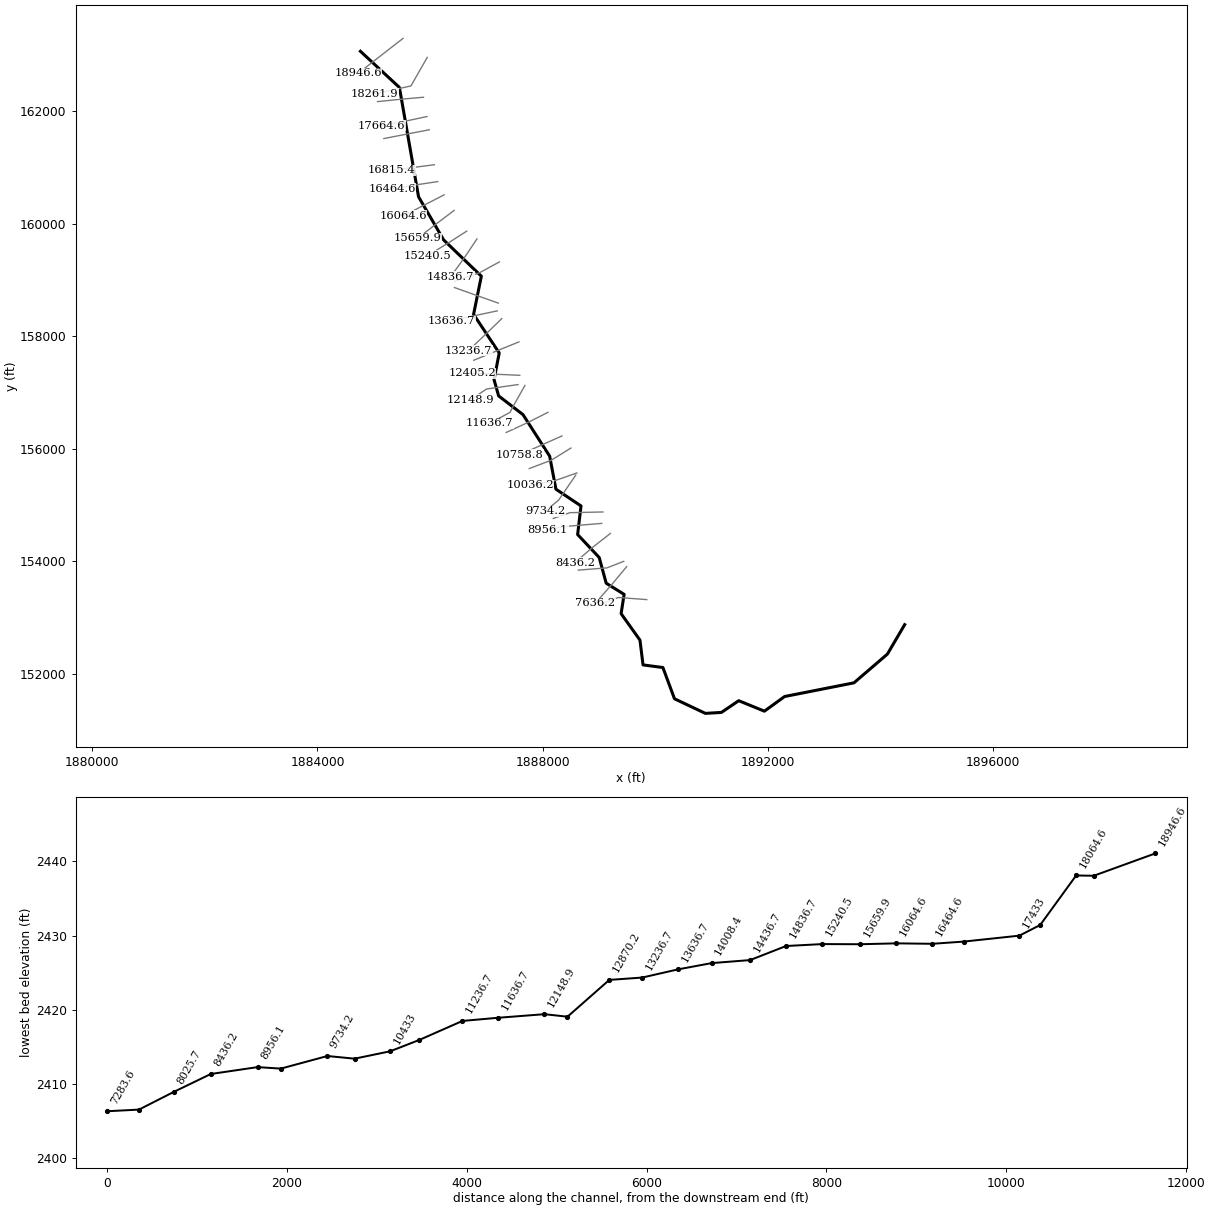
--- LfthndFrk.prj (project) ---

Proj Title=LfthndFrk
Current Plan=p01
Default Exp/Contr=0,0
English Units
Geom File=g01
Flow File=f01
Plan File=p01
BEGIN DESCRIPTION:
END DESCRIPTION:
DSS Export Rating Curves= 0
DSS Export Rating Curve Sorted= 0
DSS Export Volume Flow Curves= 0
DXF OffsetX= 0
DXF OffsetY= 0
DXF ScaleX= 0
DXF ScaleY= 0

--- LfthndFrk.p01 (plan) ---

Plan Title=Floodplain
Program Version=4.00
Geom File=g01
Flow File=f01
K Sum by GR=0
Std Step Tol=0.01
Critical Tol=0.01
Num of Std Step Trials=20
Max Error Tol=0.3
Flow Tol Ratio=0.001
Split Flow NTrial=30
Split Flow Tol=0.02
Split Flow Ratio=0.02
Log Output Level=0
Friction Slope Method=1
Unsteady Friction Slope Method=2
Unsteady Bridges Friction Slope Method=1
Global Log Level=0
CheckData=False
Run HTab=0
Run UNet=0
Run PostProcess=0
UNET Theta=0
UNET Theta Warmup=0
UNET ZTol=0
UNET ZSATol=0
UNET MxIter=0
UNET MaxInSteps=0
UNET DtIC=0
UNET DtMin=0
UNET MaxCRTS=0
UNET WFStab=0
UNET SFStab=0
UNET WFX=0
UNET SFX=0
UNET DSS MLevel=0
UNET DZMax Abort=0
UNET Convert EG Bridges=0
UNET Use Existing IB Tables=0
UNET Froude Limit=0
UNET Froude Power=0
Write IC File=0
Echo Input=False
Echo Output=False
Write Detailed=0

--- LfthndFrk.f01 (steady flow) ---

Flow Title=NFF Regression Equation
Program Version=4.00
Number of Profiles=1
Profile Names=P100yr
River Rch & RM=LfthndFrk,Main      ,18946.6
614.2113
River Rch & RM=LfthndFrk,Main      ,16815.4
661.3199
River Rch & RM=LfthndFrk,Main      ,15659.9
715.2427
River Rch & RM=LfthndFrk,Main      ,14436.7
788.7079
River Rch & RM=LfthndFrk,Main      ,10758.8
862.3187
River Rch & RM=LfthndFrk,Main      ,6836.2
953.9623
River Rch & RM=LfthndFrk,Main      ,2836.1
1055.583
River Rch & RM=LfthndFrk,Main      ,91.5
1171.700
Boundary for River Rch & Prof#=LfthndFrk,Main      ,1
Up Type=0
Dn Type=3
Dn Slope=0.004162

--- LfthndFrk.g01 (geometry) ---

Geom Title=USGS 3m DEM
Program Version=4.10

River Reach=LfthndFrk       ,Main
Reach XY= 30
     1884762.441       163058.49      1885455.26      162415.862
     1885794.625      160474.897     1886239.355      159709.542
     1886909.782      159064.742     1886771.988      158386.772
      1887227.49       157701.46     1887135.042      157227.502
     1887217.074       156938.44     1887649.365      156606.408
     1888122.858       155869.28     1888234.133      155282.569
     1888679.313      154985.315       1888619.6       154476.91
     1889002.413      154069.429     1889126.893      153612.854
     1889444.938      153415.002     1889391.553      153072.554
     1889726.188      152602.502     1889780.876      152162.398
      1890133.74      152115.523      1890339.47      151560.835
     1890887.647      151301.721     1891172.803      151318.648
     1891480.095      151526.981     1891935.824      151340.783
     1892295.199        151601.2     1893525.966      151843.914
     1894119.417      152353.804     1894426.594      152876.767

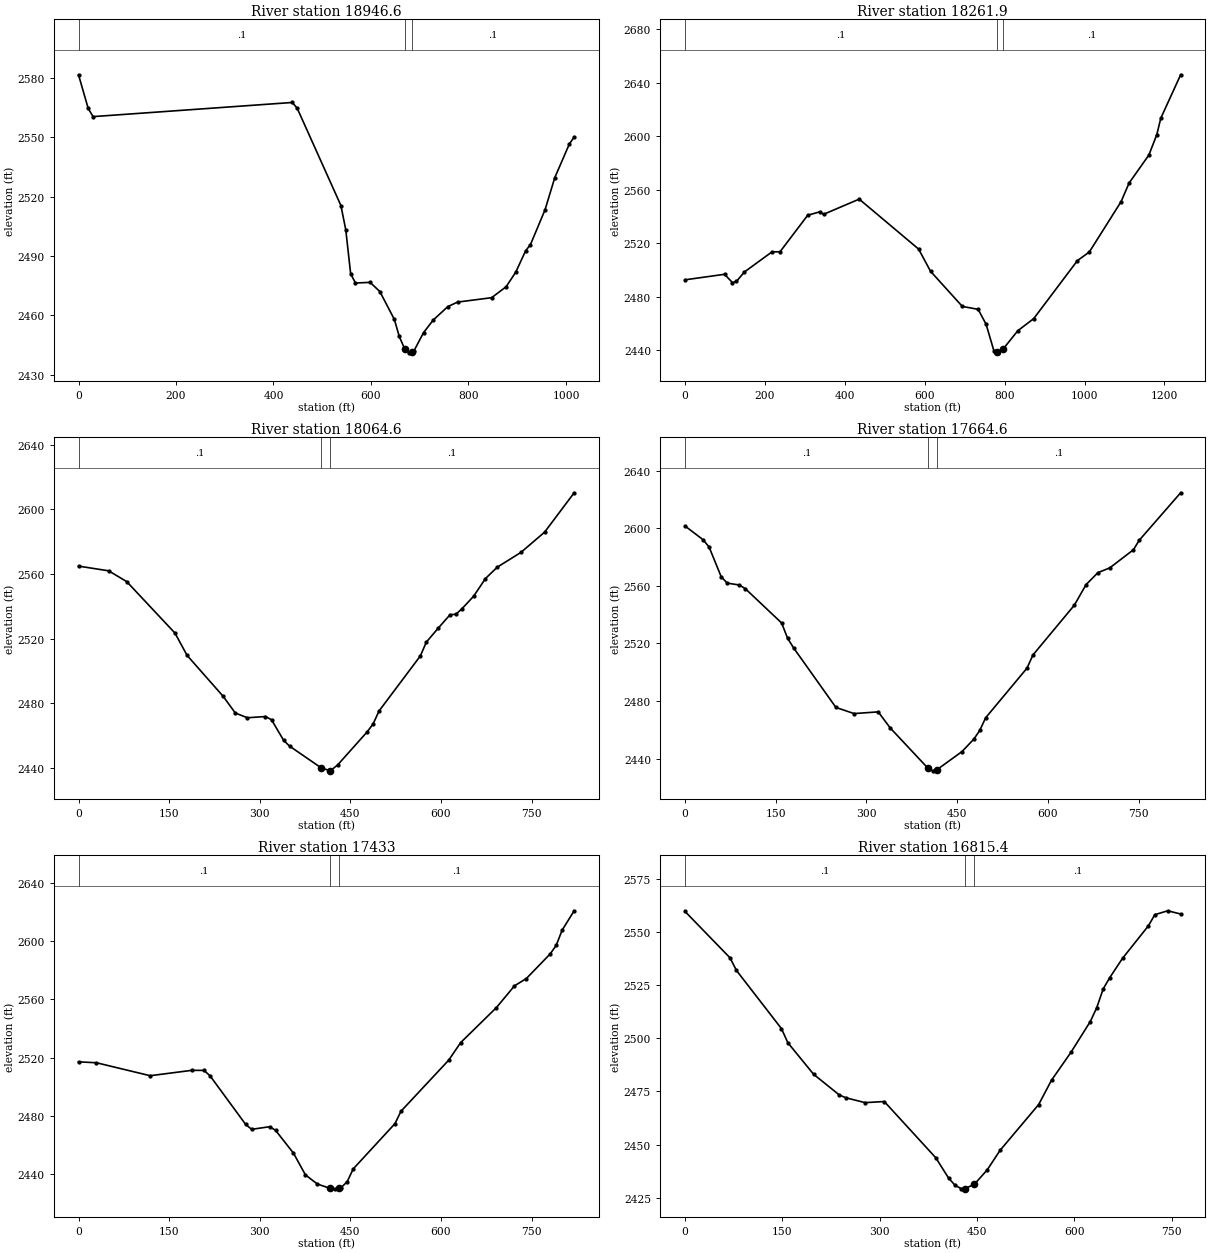
Type RM Length L Ch R = 1 ,18946.6 ,694.6,684.6,674.6
XS GIS Cut Line= 2
     1885520.301      163288.159      1884717.46      162664.124
#Sta/Elev= 30
       0 2581.58    19.9 2564.55    29.9 2560.44   438.6 2567.59   448.6 2564.67
   538.3 2515.52   548.3 2503.19   558.3 2481.02   568.2 2476.36   598.1  2476.7
   618.1 2472.08     648 2457.94     658 2449.35     669 2443.13   677.9 2441.09
     684 2441.62   687.9 2441.96   707.8  2451.3   727.7 2457.66   757.6 2464.45
   777.6 2466.73   847.4 2468.95   877.3  2474.5   897.2 2481.96   917.2 2492.65
   927.1 2495.75     957 2513.34     977 2529.58  1006.9  2546.6  1016.8 2550.12
#Mann= 3 , 0 , 0
       0      .1       0     669    .045       0     684      .1       0
Bank Sta=669,684
XS Rating Curve= 0 ,0
Exp/Cntr=0.3,0.1

Type RM Length L Ch R = 1 ,18261.9 ,198.8,196,193.4
XS GIS Cut Line= 3
     1885949.437      162950.214     1885659.368      162442.463
     1885018.587      162302.702
#Sta/Elev= 30
       0 2492.67    99.1 2496.79   118.9 2490.55   128.8 2491.45   148.7 2498.51
     218  2513.6   237.9 2513.63   307.2 2540.94     337 2543.46   346.9 2541.63
   436.1 2552.99   584.8 2515.64   614.6 2499.06   694.1  2472.8   733.8 2470.58
   753.7 2459.42   773.6 2439.19   780.7 2438.39   783.5 2438.07   795.7 2440.71
   833.2 2454.64   872.9 2463.66   982.2    2507  1012.1 2513.49  1091.6 2551.12
  1111.4 2564.94  1161.1 2585.95    1181 2601.26  1190.9 2613.44  1240.6 2645.96
#Mann= 3 , 0 , 0
       0      .1       0   780.7    .045       0   795.7      .1       0
Bank Sta=780.7,795.7
XS Rating Curve= 0 ,0
Exp/Cntr=0.3,0.1

Type RM Length L Ch R = 1 ,18064.6 ,397.1,399.9,401.7
XS GIS Cut Line= 3
       1885882.7      162242.308     1885475.068      162206.338
      1885066.11       162164.31
#Sta/Elev= 30
       0 2564.82    49.9 2561.91    79.8 2555.22   159.7 2523.35   179.7 2509.56
   239.5 2484.18   259.5 2473.89   279.5 2470.97   309.4 2471.72   319.4 2469.74
   339.4 2457.02   349.3  2453.4   401.7 2439.94   416.7 2438.11   428.8 2441.74
   477.7 2462.22   487.5 2467.08   497.3 2475.12   565.8 2509.26   575.6 2517.75
   595.2 2526.38   614.8  2534.7   624.6 2535.06   634.4 2538.34   653.9 2546.18
   673.5 2557.13   693.1 2564.18   732.2 2573.31   771.4 2585.85   820.3 2610.21
#Mann= 3 , 0 , 0
       0      .1       0   401.7    .045       0   416.7      .1       0
Bank Sta=401.7,416.7
XS Rating Curve= 0 ,0
Exp/Cntr=0.3,0.1

Type RM Length L Ch R = 1 ,17664.6 ,232.1,231.6,231.7
XS GIS Cut Line= 3
     1885944.015      161899.535     1885543.735       161813.76
      1885140.55      161737.938
#Sta/Elev= 30
       0 2601.68      30 2592.11    39.9 2587.02    59.9 2566.37    69.9 2561.94
    89.9 2560.65    99.8 2558.07   159.8 2534.24   169.7 2523.58   179.7 2516.86
   249.6  2475.5   279.6 2471.24   319.5 2472.42   339.5 2461.19   401.9 2433.19
   409.4 2431.42   416.9 2432.28   458.2 2444.86   477.7  2453.5   487.5 2459.57
   497.3 2468.39   565.6 2502.84   575.4 2511.99   643.8 2546.59   663.3 2560.94
   682.9 2569.26   702.4 2572.54   741.5 2585.14   751.2 2591.78   819.6 2624.77
#Mann= 3 , 0 , 0
       0      .1       0   401.9    .045       0   416.9      .1       0
Bank Sta=401.9,416.9
XS Rating Curve= 0 ,0
Exp/Cntr=0.3,0.1

Type RM Length L Ch R = 1 ,17433   ,618.5,617.4,616.2
XS GIS Cut Line= 2
     1885984.251      161664.653     1885178.651      161508.709
#Sta/Elev= 30
       0 2517.07    29.7 2516.44   118.6 2507.56   187.8 2511.25   207.6  2511.2
   217.5 2507.63   276.8 2474.12   286.7 2470.79   316.4 2472.58   326.2 2470.12
   355.9 2454.44   375.7 2439.54   395.4 2433.29   416.2 2430.34   425.1 2429.98
   431.2 2430.54     435 2430.89   444.9 2434.95   454.8 2443.66     524 2474.73
   533.8 2483.15   612.9 2518.23   632.7 2530.26     692 2554.32   721.7 2569.16
   741.5 2574.22     781 2591.12   790.9 2596.99   800.8 2607.49   820.6 2620.66
#Mann= 3 , 0 , 0
       0      .1       0   416.2    .045       0   431.2      .1       0
Bank Sta=416.2,431.2
XS Rating Curve= 0 ,0
Exp/Cntr=0.3,0.1

Type RM Length L Ch R = 1 ,16815.4 ,350.5,350.7,349.8
XS GIS Cut Line= 3
     1886075.747      161043.885     1885535.304      160974.151
     1885318.054      160948.671
#Sta/Elev= 30
       0 2559.54    69.4 2537.72    79.3  2531.8   148.6 2504.49   158.5 2497.83
   198.2 2483.01   237.8 2473.29   247.7    2472   277.4 2469.68   307.1 2470.21
   386.4 2443.79   406.2 2434.22   416.1 2430.87     426 2429.18   430.8 2429.23
   445.8 2431.29   465.7 2438.09   485.5 2447.27   544.9 2468.77   564.8 2480.25
   594.6 2493.28   624.5 2507.78   634.4 2514.27   644.4 2523.14   654.3 2528.33
   674.2 2537.52     714 2552.75   723.9    2558   743.8 2559.84   763.7 2558.32
#Mann= 3 , 0 , 0
       0      .1       0   430.8    .045       0   445.8      .1       0
Bank Sta=430.8,445.8
XS Rating Curve= 0 ,0
Exp/Cntr=0.3,0.1

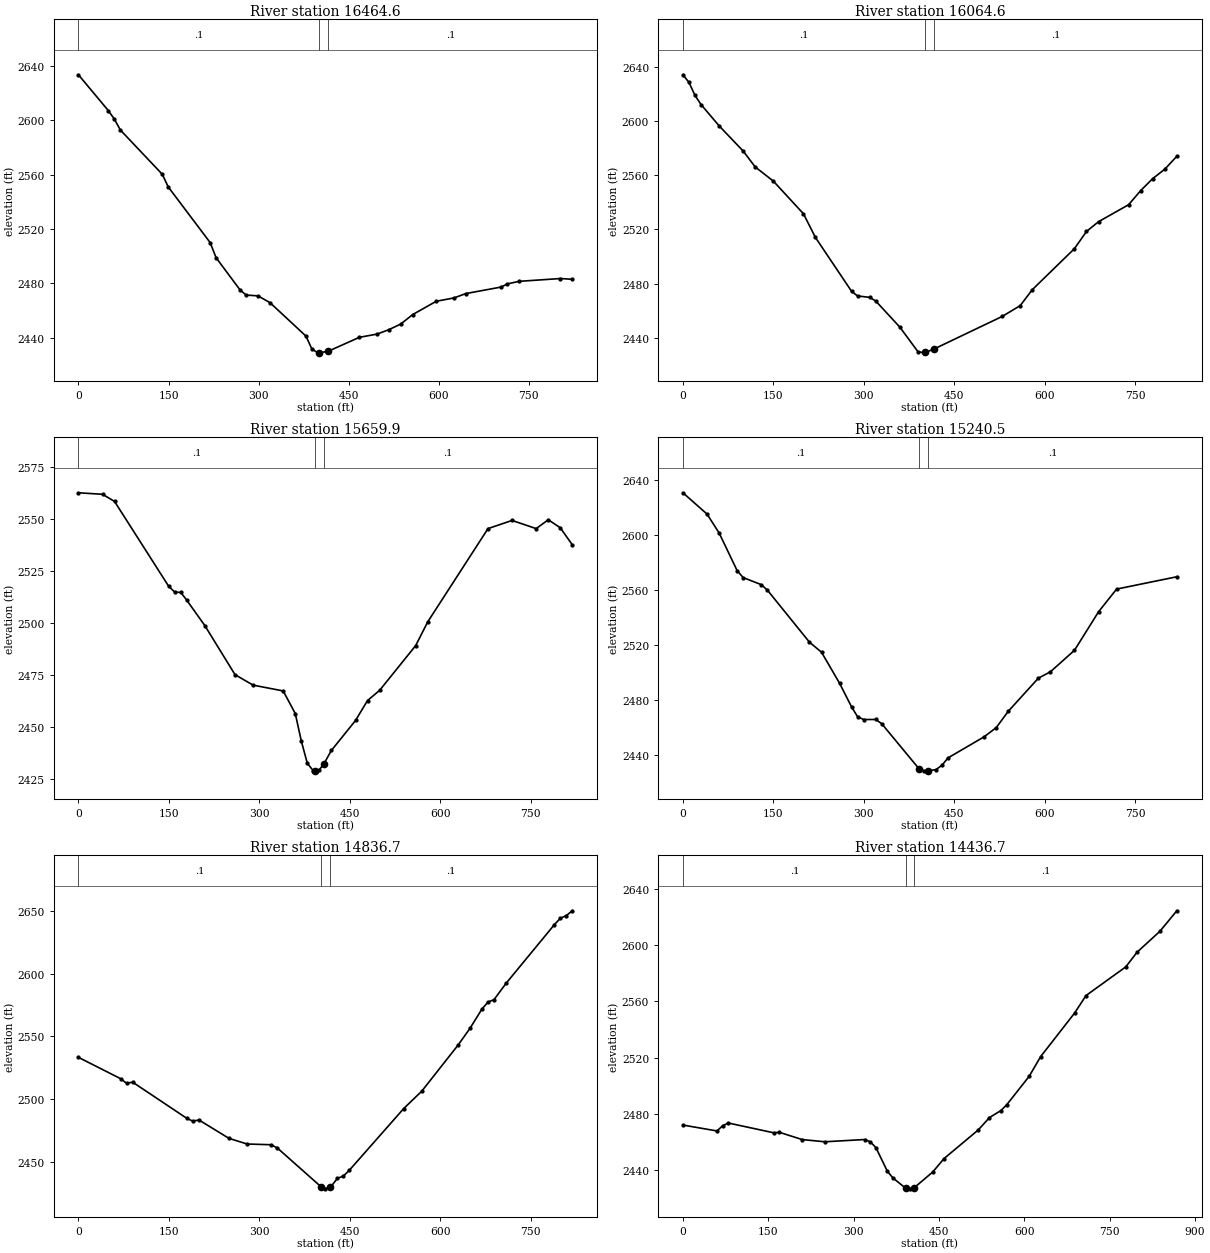
Type RM Length L Ch R = 1 ,16464.6 ,392.7,400,406.8
XS GIS Cut Line= 3
     1886135.426      160744.651     1885731.393      160683.251
       1885323.9      160612.114
#Sta/Elev= 30
       0 2633.43    49.8 2607.07    59.8 2600.85    69.8 2592.81   139.6 2560.24
   149.5 2550.94   219.3    2510   229.2 2498.85   269.1 2475.18   279.1 2471.41
     299 2470.78     319 2465.77   378.8 2441.21   388.7  2431.7   398.7 2428.88
   401.2  2428.9   416.2 2430.11   467.8  2440.3   497.3 2442.67     517 2445.95
   536.7 2450.07   556.4 2456.98   595.8 2466.82   625.4 2469.28     645 2472.48
   704.1  2477.3     714 2479.58   733.7 2481.48   802.6 2483.54   822.3 2482.98
#Mann= 3 , 0 , 0
       0      .1       0   401.2    .045       0   416.2      .1       0
Bank Sta=401.2,416.2
XS Rating Curve= 0 ,0
Exp/Cntr=0.3,0.1

Type RM Length L Ch R = 1 ,16064.6 ,400.6,404.7,408.8
XS GIS Cut Line= 3
     1886249.465      160509.088      1885885.27      160321.865
     1885521.076      160134.641
#Sta/Elev= 30
       0 2633.97      10 2628.34      20 2618.76      30 2612.04    59.9 2596.36
    99.9 2577.71   119.8 2566.02   149.8 2555.62   199.8 2531.51   219.7 2514.02
   279.7 2474.26   289.6 2470.88   309.6 2469.86   319.6  2467.2   359.6 2447.95
   389.5 2429.91   399.5 2428.94     402 2429.22     417  2431.9   529.4 2455.78
   559.3 2463.76   579.3  2475.5   649.2 2505.76   669.2 2518.44   689.2 2525.65
   739.1 2538.18   759.1 2548.61     779 2557.41     799 2564.34     819 2573.88
#Mann= 3 , 0 , 0
       0      .1       0     402    .045       0     417      .1       0
Bank Sta=402,417
XS Rating Curve= 0 ,0
Exp/Cntr=0.3,0.1

Type RM Length L Ch R = 1 ,15659.9 ,420.6,419.3,418.3
XS GIS Cut Line= 3
     1886426.634      160232.938     1886100.148      159985.721
     1885776.056      159735.419
#Sta/Elev= 30
       0 2562.68      40 2561.95    59.9 2558.51   149.8 2517.61   159.8 2514.85
   169.8 2514.71   179.8 2510.91   209.8 2498.67   259.7 2475.11   289.7 2470.08
   339.6 2467.28   359.6  2456.4   369.6 2443.16   379.6 2432.43   389.6 2428.82
   391.8 2428.94   399.5 2429.34   406.8 2432.04   419.5 2438.64   459.5 2453.06
   479.4 2462.66   499.4 2467.55   559.3 2489.12   579.3 2500.56   679.2 2545.44
   719.1 2549.36   759.1 2545.43   779.1  2549.7     799 2545.85     819 2537.64
#Mann= 3 , 0 , 0
       0      .1       0   391.8    .045       0   406.8      .1       0
Bank Sta=391.8,406.8
XS Rating Curve= 0 ,0
Exp/Cntr=0.3,0.1

Type RM Length L Ch R = 1 ,15240.5 ,393.9,403.1,411.2
XS GIS Cut Line= 3
     1886650.351       159865.01     1886305.638       159643.71
     1885955.996      159430.587
#Sta/Elev= 30
       0 2630.95      40 2615.45      60 2601.72    89.9 2574.36    99.9  2569.3
   129.9 2564.18   139.9 2560.27   209.8 2522.37   229.8 2515.07   259.8 2492.47
   279.8 2475.21   289.7 2468.13   299.7 2466.13   319.7 2466.17   329.7 2463.09
   391.4 2430.41   399.6 2428.84   406.4 2428.84   419.6 2429.72   429.6 2432.91
   439.6 2438.24   499.5 2453.58   519.5 2460.21   539.5 2472.09   589.4 2496.19
   609.4 2500.82   649.3 2516.42   689.3 2544.45   719.2 2560.94   819.1  2569.9
#Mann= 3 , 0 , 0
       0      .1       0   391.4    .045       0   406.4      .1       0
Bank Sta=391.4,406.4
XS Rating Curve= 0 ,0
Exp/Cntr=0.3,0.1

Type RM Length L Ch R = 1 ,14836.7 ,410.8,399.9,386.2
XS GIS Cut Line= 3
     1886831.656      159726.055     1886603.495      159385.989
     1886363.849      159053.794
#Sta/Elev= 30
       0 2533.34    69.9 2516.36    79.9 2512.62    89.9 2513.58   179.8 2484.74
   189.8 2482.47   199.8 2483.46   249.7  2468.8   279.7  2464.3   319.6 2463.71
   329.6 2461.25     402  2430.4   409.5 2428.58     417 2430.22   419.5 2430.76
   429.5  2436.9   439.5 2438.79   449.5  2443.5   539.4  2492.5   569.4 2506.38
   629.3 2542.89   649.3 2556.37   669.3 2571.84   679.3 2577.39   689.2 2579.26
   709.2  2592.3   789.2 2638.96   799.2  2644.1   809.1 2646.29   819.1 2650.11
#Mann= 3 , 0 , 0
       0      .1       0     402    .045       0     417      .1       0
Bank Sta=402,417
XS Rating Curve= 0 ,0
Exp/Cntr=0.3,0.1

Type RM Length L Ch R = 1 ,14436.7 ,447.1,428.3,413.3
XS GIS Cut Line= 3
      1887230.01      159317.745     1886879.475      159127.103
     1886436.759       158972.69
#Sta/Elev= 30
       0 2472.02    59.8 2467.83    69.8 2471.54    79.8 2473.47   159.6 2466.52
   169.6 2466.85   209.5 2461.71   249.4 2460.14   319.2 2461.74   329.2 2460.15
   339.2 2455.92   359.1 2439.25   369.1 2434.37   391.5 2427.11     399 2426.68
   406.5  2427.5   438.9 2438.63   458.9 2448.23   518.7 2468.46   538.7 2477.36
   558.6 2482.29   568.6 2486.25   608.5 2506.72   628.5 2520.64   688.3 2551.68
   708.3 2564.09   778.1 2584.44   798.1 2594.93     838 2609.71   867.9 2624.36
#Mann= 3 , 0 , 0
       0      .1       0   391.5    .045       0   406.5      .1       0
Bank Sta=391.5,406.5
XS Rating Curve= 0 ,0
Exp/Cntr=0.3,0.1

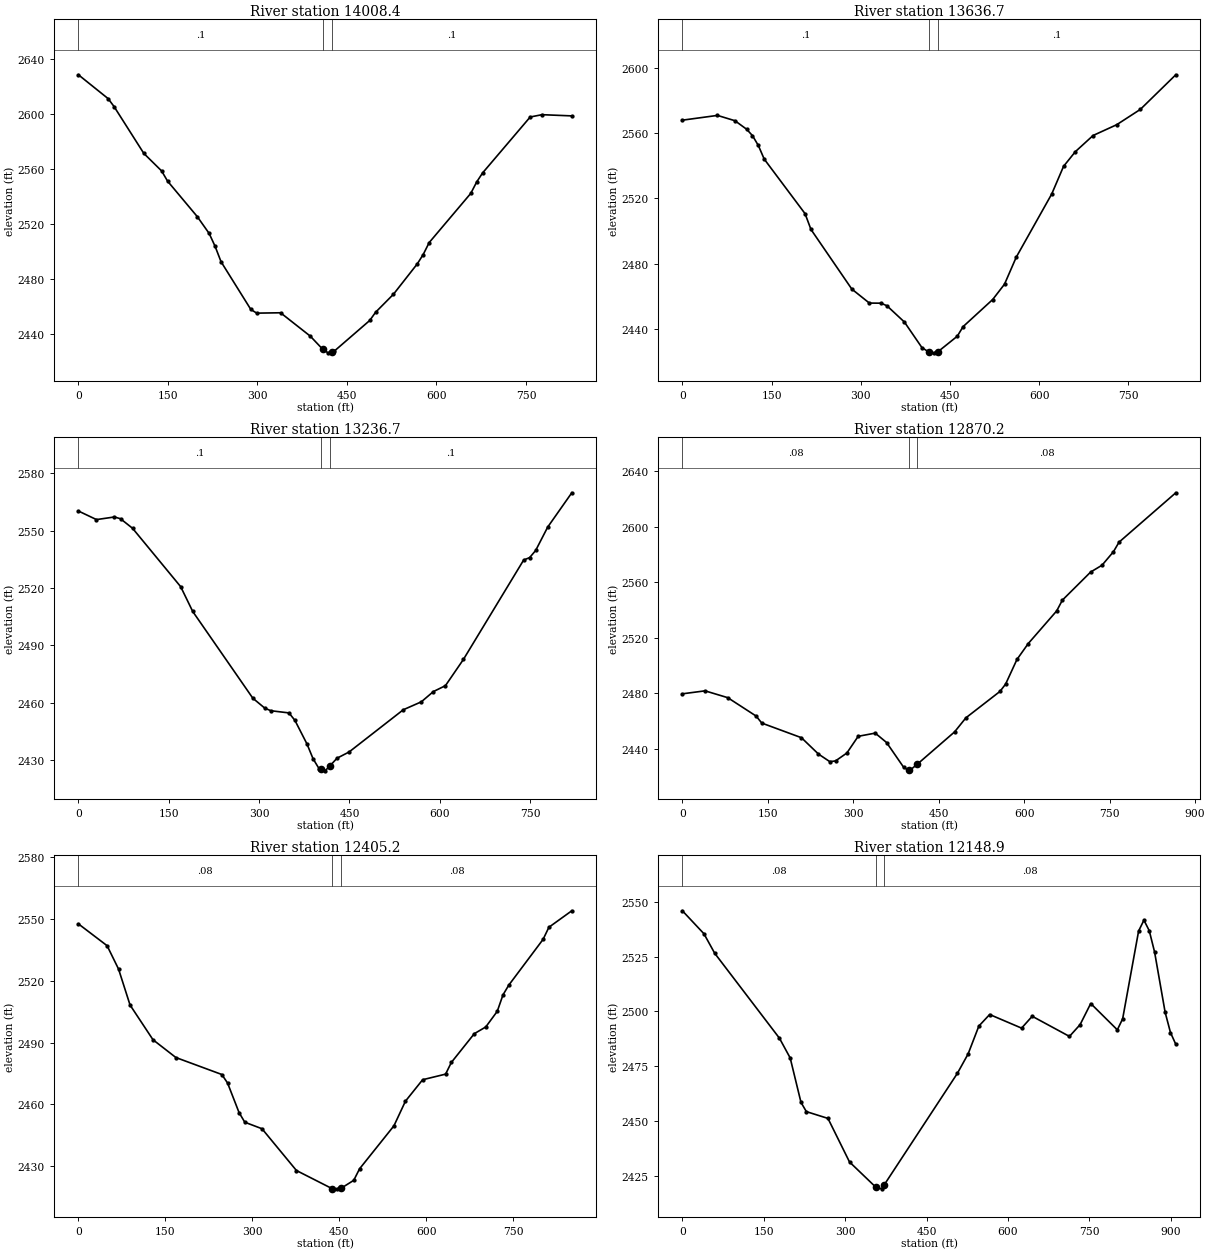
Type RM Length L Ch R = 1 ,14008.4 ,359.1,371.6,384.7
XS GIS Cut Line= 2
     1887211.041      158586.434     1886431.948      158863.003
#Sta/Elev= 30
       0 2628.42    49.8 2611.09    59.8 2605.29   109.6 2571.27   139.4 2558.53
   149.4 2551.11   199.2 2525.29   219.1 2513.06   229.1 2503.64     239 2492.51
   288.9 2457.82   298.8 2455.13   338.7  2455.4   388.5 2438.42   409.3  2428.9
   418.3 2426.27   424.3 2426.92   428.3 2427.36   488.1 2449.79     498 2455.79
   527.9 2468.87   567.8 2490.94   577.7 2497.72   587.7 2506.41   657.4 2542.18
   667.4 2550.53   677.3  2557.1     757 2597.73   776.9 2599.41   826.7 2598.53
#Mann= 3 , 0 , 0
       0      .1       0   409.3    .045       0   424.3      .1       0
Bank Sta=409.3,424.3
XS Rating Curve= 0 ,0
Exp/Cntr=0.3,0.1

Type RM Length L Ch R = 1 ,13636.7 ,387.3,399.9,411.9
XS GIS Cut Line= 3
       1887191.4       158448.62     1886778.116       158360.98
     1886381.933      158266.855
#Sta/Elev= 30
       0 2567.92      59 2570.84    88.4 2567.58   108.1 2562.35   117.9 2558.43
   127.7 2552.43   137.6 2544.09   206.3 2510.66   216.2 2501.01   284.9 2464.48
   314.4 2455.91     334 2455.84   343.9 2454.28   373.4 2444.28   402.8 2428.64
     415 2425.79   422.5 2425.43     430 2426.18   462.2 2435.58   472.1  2441.5
   521.8 2458.08   541.7 2467.48   561.5 2484.07   621.1 2522.72     641 2539.66
   660.8 2548.63   690.6 2558.53   730.4 2565.15   770.1 2574.52   829.7 2595.72
#Mann= 3 , 0 , 0
       0      .1       0     415    .045       0     430      .1       0
Bank Sta=415,430
XS Rating Curve= 0 ,0
Exp/Cntr=0.3,0.1

Type RM Length L Ch R = 1 ,13236.7 ,375.7,366.6,357.5
XS GIS Cut Line= 3
     1887273.039      158311.663     1886978.826      158026.873
     1886682.292      157744.311
#Sta/Elev= 30
       0 2560.28      30 2555.79    59.9 2557.16    69.9 2556.23    89.9 2551.24
   169.8 2520.68   189.8 2507.71   289.6 2462.31   309.6 2457.09   319.6 2455.77
   349.6 2454.63   359.5  2450.7   379.5 2438.36   389.5  2430.7   399.5 2425.46
     402 2425.18   409.5 2424.32     417 2426.75   429.4 2430.94   449.4 2434.19
   539.4 2456.29   569.3 2460.43   589.3  2465.8   609.3 2468.88   639.2 2482.63
   739.2 2534.64   749.1  2535.9   759.1 2539.62   779.1 2551.87   819.1 2569.82
#Mann= 3 , 0 , 0
       0      .1       0     402    .045       0     417      .1       0
Bank Sta=402,417
XS Rating Curve= 0 ,0
Exp/Cntr=0.3,0.1

Type RM Length L Ch R = 1 ,12870.2 ,474.2,464.9,455.6
XS GIS Cut Line= 2
     1887576.849      157897.787     1886774.434       157571.91
#Sta/Elev= 30
       0  2479.5    39.8 2481.64    79.6 2476.73   129.4 2463.48   139.4 2458.41
     209 2447.87   238.9 2436.08   258.8 2430.62   268.8 2431.14   288.7 2436.83
   308.6 2448.88   338.5 2451.18   358.4 2444.42   388.2 2426.68     397 2424.32
   398.2    2424     412 2428.65   477.8 2452.06   497.7 2462.21   557.5 2481.23
   567.4 2486.52   587.3 2504.26   607.2 2515.75     657 2539.22     667 2546.99
   716.7 2567.26   736.6 2572.16   756.6 2581.84   766.5 2588.78   866.1 2624.36
#Mann= 3 , 0 , 0
       0     .08       0     397    .045       0     412     .08       0
Bank Sta=397,412
XS Rating Curve= 0 ,0
Exp/Cntr=0.3,0.1

Type RM Length L Ch R = 1 ,12405.2 ,251.4,256.3,261.6
XS GIS Cut Line= 2
     1887591.971      157304.761     1886741.696      157342.984
#Sta/Elev= 30
       0 2547.64    49.5 2537.05    69.3 2525.68    89.1 2508.25   128.7 2491.39
   168.2 2482.76   247.4 2474.53   257.3  2470.4   277.1 2456.07     287 2451.37
   316.7  2448.2   376.1 2427.93     438 2419.08   445.4 2419.03     453 2419.29
     475 2423.17     485 2428.75   544.3 2449.62   564.1 2461.56   593.8 2471.99
   633.4 2474.71   643.3 2480.37   682.9 2494.34   702.7 2497.61   722.5 2505.19
   732.4 2513.18   742.3 2517.87   801.6 2540.14   811.6    2546   851.1    2554
#Mann= 3 , 0 , 0
       0     .08       0     438    .045       0     453     .08       0
Bank Sta=438,453
XS Rating Curve= 0 ,0
Exp/Cntr=0.3,0.1

Type RM Length L Ch R = 1 ,12148.9 ,491.5,512.1,531.7
XS GIS Cut Line= 3
     1887561.629      157140.092     1887001.071       157060.97
     1886716.768        156869.2
#Sta/Elev= 30
       0 2545.79    39.7 2535.35    59.6 2526.45   178.8 2487.86   198.6 2478.88
   218.5 2458.68   228.4 2454.48   268.2 2451.39   307.9 2431.59   356.7 2420.04
   367.5 2419.37   371.7 2421.13   506.5 2471.83   526.4  2480.7   546.2 2493.38
   566.1 2498.63   624.9 2492.44   644.5 2497.83   713.1 2488.67   732.7 2494.02
   752.3 2503.63   801.3 2491.66   811.1 2496.66   840.5 2536.58   850.3 2541.53
   860.1 2536.75   869.9 2527.09   889.4 2499.62   899.2 2490.44     909 2485.09
#Mann= 3 , 0 , 0
       0     .08       0   356.7    .045       0   371.7     .08       0
Bank Sta=356.7,371.7
XS Rating Curve= 0 ,0
Exp/Cntr=0.3,0.1

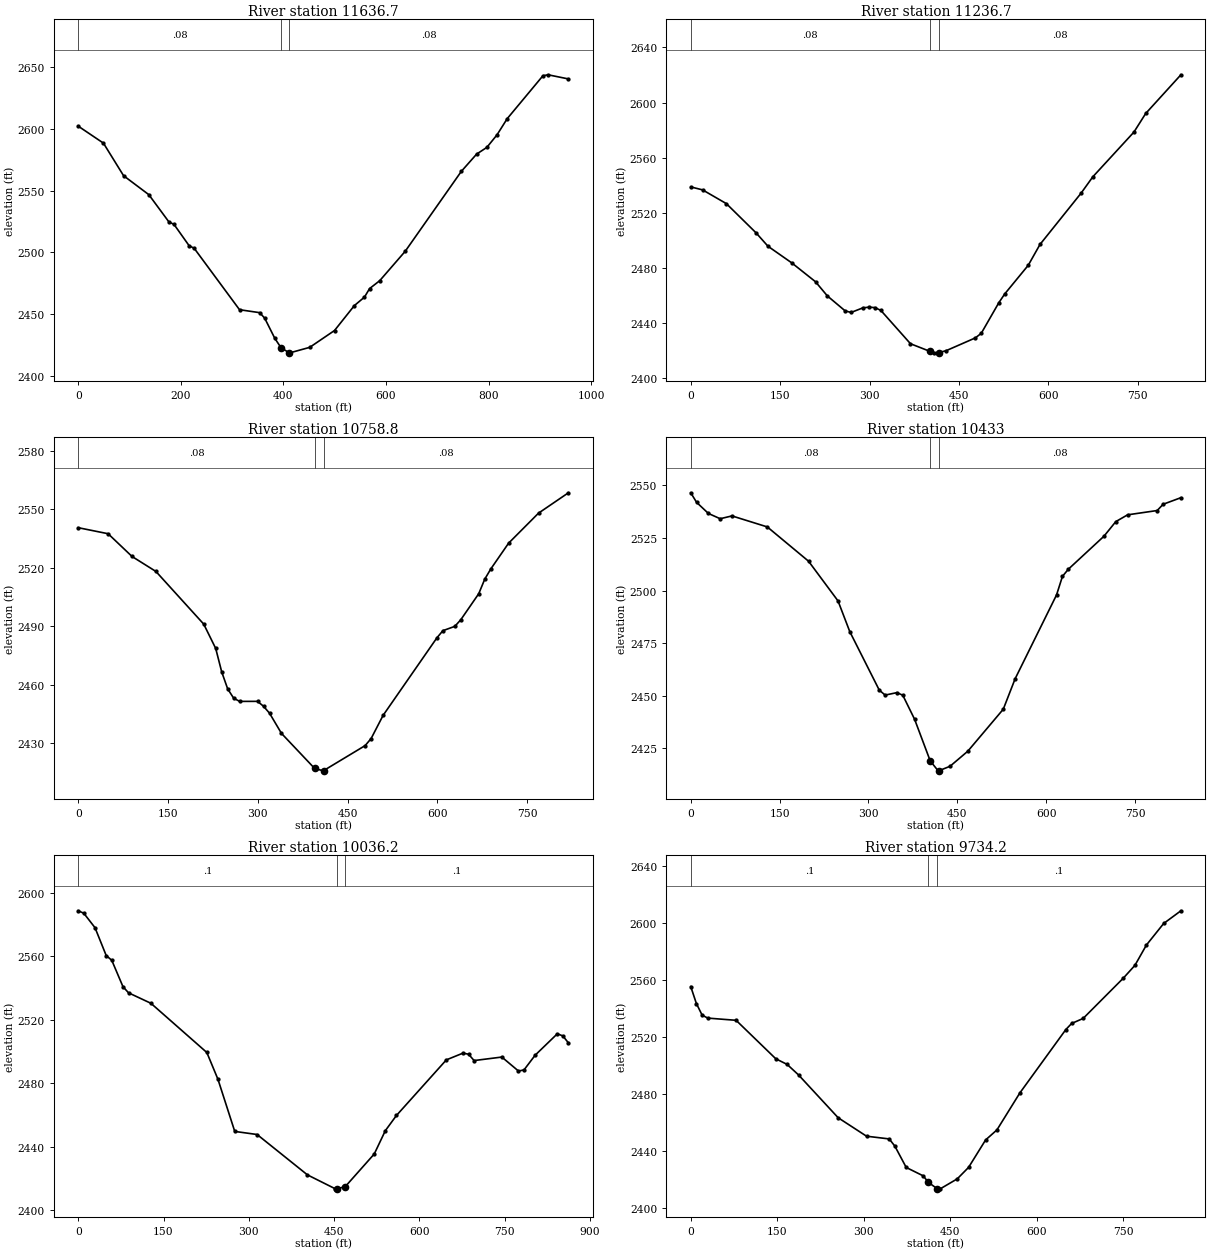
Type RM Length L Ch R = 1 ,11636.7 ,413.2,400,386.4
XS GIS Cut Line= 4
      1887683.92      157125.039     1887485.811      156774.295
     1887417.926      156645.988     1887058.736      156453.475
#Sta/Elev= 30
       0 2601.97    49.1 2588.26    88.4 2561.95   137.6 2546.64   176.8 2524.61
   186.7 2522.63   216.2 2505.38     226 2503.35   314.4 2453.72   353.7 2451.34
   363.5 2446.86   383.2 2430.58   395.3 2423.04   410.3 2419.16   412.5 2418.89
   451.2 2423.32   499.6 2436.93   538.3 2457.07   557.9 2463.87   567.9 2470.77
   587.7 2477.17   637.4 2500.92   746.8 2565.47   776.6 2579.41   796.5 2584.82
   816.4 2594.99   836.2 2608.02   905.8 2642.67   915.8 2643.47   955.5 2640.12
#Mann= 3 , 0 , 0
       0     .08       0   395.3    .045       0   410.3     .08       0
Bank Sta=395.3,410.3
XS Rating Curve= 0 ,0
Exp/Cntr=0.3,0.1

Type RM Length L Ch R = 1 ,11236.7 ,478.9,478,478
XS GIS Cut Line= 3
     1888091.786      156646.917     1887727.136      156462.284
     1887350.895      156289.855
#Sta/Elev= 30
       0 2538.85    19.9 2536.69    59.8 2526.71   109.7 2505.49   129.6  2495.8
   169.5 2483.74   209.4 2470.04   229.3 2459.74   259.2 2448.88   269.2 2447.78
   289.1 2451.13   299.1 2451.57     309  2451.3     319 2449.27   368.8 2425.06
   401.2 2419.57   408.7 2418.46   416.2 2418.68   428.4 2419.98   477.7 2429.31
   487.6 2432.66   517.1 2454.87     527 2461.23   566.4 2481.98   586.1 2497.09
   655.1 2534.32   674.8 2546.19   743.8 2578.64   763.5 2592.11   822.6  2620.2
#Mann= 3 , 0 , 0
       0     .08       0   401.2    .045       0   416.2     .08       0
Bank Sta=401.2,416.2
XS Rating Curve= 0 ,0
Exp/Cntr=0.3,0.1

Type RM Length L Ch R = 1 ,10758.8 ,323.1,325.7,324.4
XS GIS Cut Line= 3
     1888340.983      156227.869     1887966.773      156061.572
     1887593.901       155892.25
#Sta/Elev= 30
       0 2540.47    49.9 2537.38    89.9 2525.72   129.8 2518.05   209.7 2491.06
   229.7  2478.6   239.7  2466.6   249.7 2457.88   259.7 2453.12   269.7 2451.48
   299.6  2451.5   309.6 2448.98   319.6 2445.44   339.6 2435.08     395 2417.12
   409.5  2415.9     410 2416.02   479.4 2428.84   489.4 2432.46   509.4 2444.33
   599.3 2484.05   609.3 2487.72   629.2 2489.92   639.2 2493.32   669.2 2506.66
   679.2 2514.09   689.2 2519.28   719.1 2532.55   769.1 2547.93     819 2558.36
#Mann= 3 , 0 , 0
       0     .08       0     395    .045       0     410     .08       0
Bank Sta=395,410
XS Rating Curve= 0 ,0
Exp/Cntr=0.3,0.1

Type RM Length L Ch R = 1 ,10433   ,400.1,396.6,392.1
XS GIS Cut Line= 3
     1888499.865      156013.336     1888153.703      155798.079
     1887761.492        155648.9
#Sta/Elev= 30
       0 2546.47     9.9 2541.92    29.8 2536.65    49.7 2534.14    69.6 2535.48
   129.2 2530.25   198.8 2513.97   248.6 2495.08   268.4 2480.52   318.2 2452.71
   328.1 2450.35     348 2451.52   357.9 2450.28   377.8 2438.87   404.2 2419.08
   417.6 2414.36   419.2 2414.45   437.6 2416.52   467.6 2423.68   527.5 2443.64
   547.5 2458.11   617.4 2497.93   627.4 2506.77   637.4 2510.18   697.4 2525.82
   717.4 2532.77   737.3 2535.99   787.3 2538.04   797.3 2541.01   827.3 2544.14
#Mann= 3 , 0 , 0
       0     .08       0   404.2    .045       0   419.2     .08       0
Bank Sta=404.2,419.2
XS Rating Curve= 0 ,0
Exp/Cntr=0.3,0.1

Type RM Length L Ch R = 1 ,10036.2 ,288.5,301.9,320.1
XS GIS Cut Line= 3
     1888605.958      155570.693     1888169.828      155417.852
     1887775.106      155352.683
#Sta/Elev= 30
       0  2588.7     9.8 2587.14    29.5 2578.03    49.2 2560.47      59 2557.47
    78.7 2540.82    88.5 2536.96   127.8 2530.37   226.2 2499.34   245.8  2482.4
   275.3 2449.57   314.6 2447.62   403.1 2422.18   452.3 2413.36   454.6 2413.36
   469.6 2414.72   520.7 2435.35   540.2 2450.05   559.7 2459.61   647.5 2494.68
   676.8 2498.94   686.6 2498.25   696.3 2494.25   745.1 2496.46   774.4 2487.64
   784.1 2488.35   803.7 2497.63   842.7 2511.13   852.4  2509.8   862.2 2505.41
#Mann= 3 , 0 , 0
       0      .1       0   454.6    .045       0   469.6      .1       0
Bank Sta=454.6,469.6
XS Rating Curve= 0 ,0
Exp/Cntr=0.3,0.1

Type RM Length L Ch R = 1 ,9734.2  ,539.7,517.8,495.9
XS GIS Cut Line= 3
     1888586.492      155533.036     1888280.643      155086.581
     1888040.417       154891.73
#Sta/Elev= 30
       0 2555.46     9.8 2543.56    19.7 2535.49    29.5 2533.36    78.7 2531.81
   147.6 2504.85   167.3  2500.9     187 2493.56   255.8 2463.53     305 2450.61
   344.4 2448.69   354.2 2443.64   373.9  2428.7   403.4 2422.81   412.4 2418.24
   427.4 2413.88   432.9 2413.72   462.4  2420.7   482.1 2428.76   511.6 2447.96
   531.3 2455.02   571.1 2480.94   650.9 2525.37   660.9  2529.6   680.9 2533.13
   750.7  2561.4   770.7 2570.31   790.6 2584.53   820.6 2599.66   850.5 2608.56
#Mann= 3 , 0 , 0
       0      .1       0   412.4    .045       0   427.4      .1       0
Bank Sta=412.4,427.4
XS Rating Curve= 0 ,0
Exp/Cntr=0.3,0.1

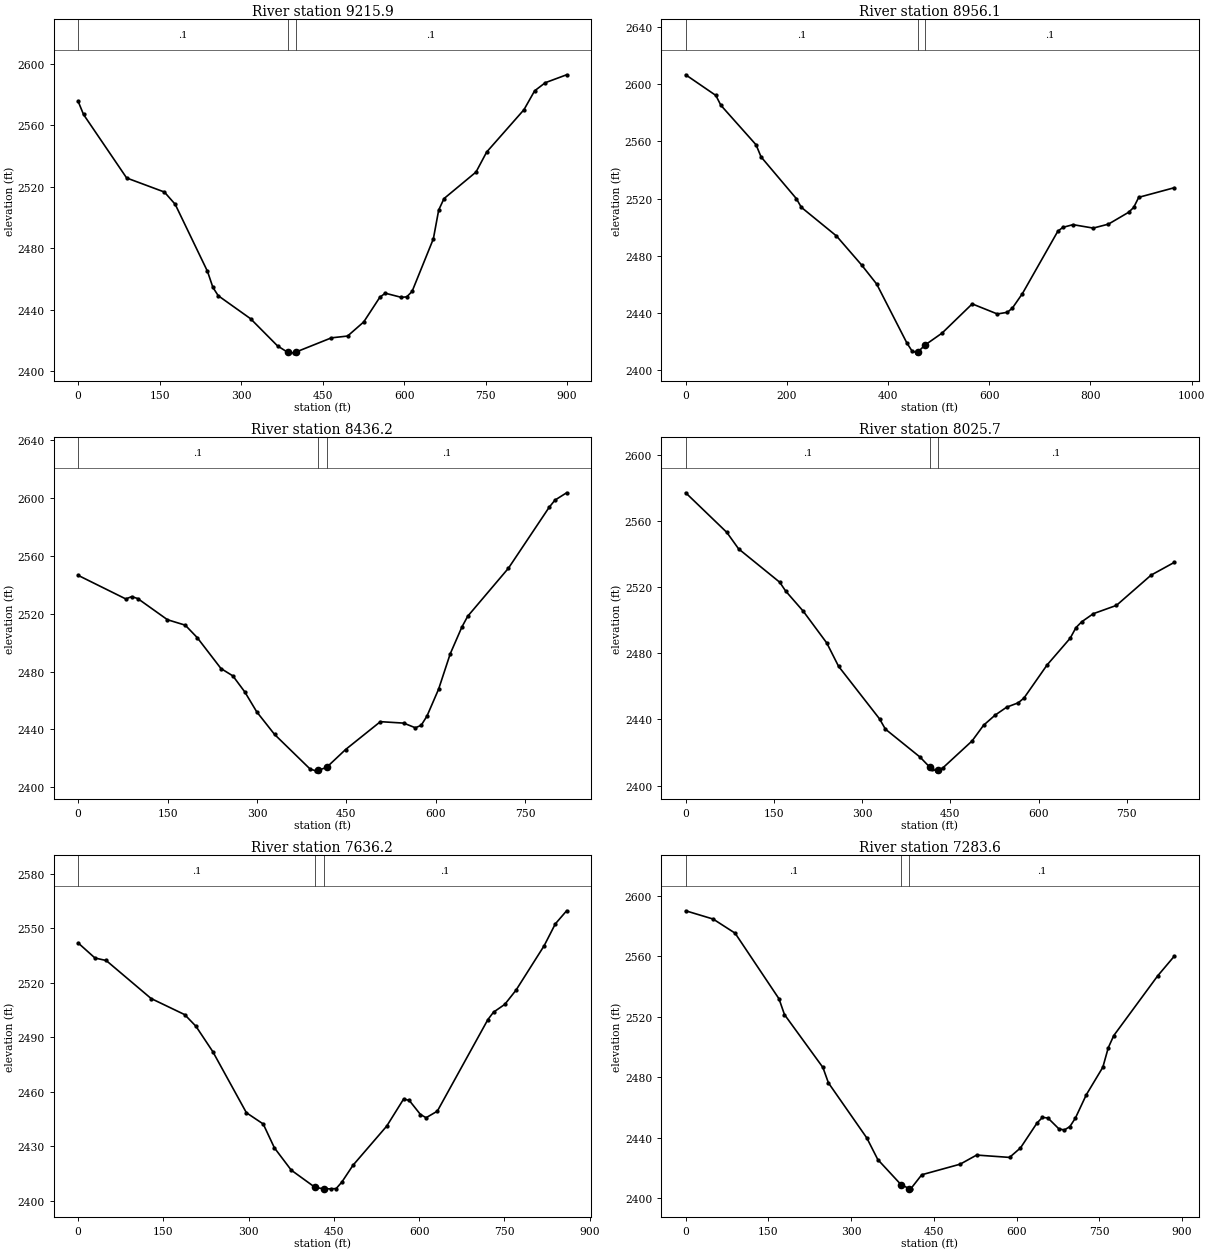
Type RM Length L Ch R = 1 ,9215.9  ,257.8,259.5,261.3
XS GIS Cut Line= 3
     1889069.046      154878.063     1888483.936      154865.673
     1888187.099       154763.45
#Sta/Elev= 30
       0 2575.58     9.9 2567.03    89.3 2525.74   158.7 2516.61   178.6 2508.65
   238.1    2465     248 2454.62   257.9 2449.16   317.4 2434.21     367 2416.55
   385.7 2412.37   396.8 2412.02   400.7 2412.51   466.2 2421.77     496 2422.94
   525.7 2432.11   555.5 2448.24   565.4  2450.8     595  2448.1   604.9 2448.45
   614.7 2451.94   653.9 2486.19   663.7  2504.9   673.5 2512.34   732.4  2529.6
     752 2542.61   820.7 2570.16   840.3 2582.42   859.9  2587.7   899.2 2592.86
#Mann= 3 , 0 , 0
       0      .1       0   385.7    .045       0   400.7      .1       0
Bank Sta=385.7,400.7
XS Rating Curve= 0 ,0
Exp/Cntr=0.3,0.1

Type RM Length L Ch R = 1 ,8956.1  ,506.7,519.9,534.1
XS GIS Cut Line= 3
     1889048.517      154675.244     1888375.311       154618.92
     1888091.008      154562.596
#Sta/Elev= 30
       0  2606.4    59.6 2591.98    69.5 2585.12   139.1  2557.5     149 2549.05
   218.6 2519.96   228.5 2513.87     298 2493.84   347.7 2473.57   377.5 2460.25
   437.1 2419.15   447.1 2413.64     457 2412.22   458.5 2412.69   473.5 2417.78
   506.7    2426   566.3  2446.4     616 2439.36   635.8 2440.54   645.8 2443.53
   665.6 2453.64   735.5 2497.14   745.5 2499.85   765.5 2501.73   805.5 2499.34
   835.5  2502.1   875.4 2510.37   885.4 2513.74   895.4 2520.82   965.4  2527.5
#Mann= 3 , 0 , 0
       0      .1       0   458.5    .045       0   473.5      .1       0
Bank Sta=458.5,473.5
XS Rating Curve= 0 ,0
Exp/Cntr=0.3,0.1

Type RM Length L Ch R = 1 ,8436.2  ,423.7,410.4,396.2
XS GIS Cut Line= 3
     1889201.743       154497.38     1888879.525      154244.811
     1888568.664      153977.459
#Sta/Elev= 30
       0 2546.62    79.9  2530.3    89.9  2531.9    99.9 2530.58   149.8 2515.91
   179.7 2512.13   199.7 2503.54   239.6 2482.11   259.6    2477   279.6 2465.88
   299.6 2452.12   329.5 2436.49   389.4 2412.42   399.4 2411.29   401.9 2411.53
   416.9 2413.72   448.5    2426     507 2445.33   546.1 2444.33   565.6 2441.11
   575.4 2442.79   585.1 2449.17   604.6 2467.78   624.2 2492.36   643.7 2510.84
   653.5 2518.33   721.8 2551.57   790.1 2593.74   799.9 2598.73   819.4 2603.79
#Mann= 3 , 0 , 0
       0      .1       0   401.9    .045       0   416.9      .1       0
Bank Sta=401.9,416.9
XS Rating Curve= 0 ,0
Exp/Cntr=0.3,0.1

Type RM Length L Ch R = 1 ,8025.7  ,371.4,388.5,404.7
XS GIS Cut Line= 3
     1889437.841      154001.154     1889139.709      153885.366
     1888630.639       153845.54
#Sta/Elev= 30
       0 2577.24      70 2553.24      90 2543.27   159.9 2523.07   169.9 2517.77
   199.9 2505.52   239.9 2486.27   259.9 2472.17   329.6 2440.32   339.5 2434.14
   398.4 2417.21   414.6 2411.24     418 2409.78   427.8 2408.88   429.6 2409.23
   437.7 2410.83   486.8 2426.95   506.4 2436.48     526  2442.6   545.7 2447.43
   565.3 2450.06   575.1 2452.95   614.4 2472.99   653.7  2489.2   663.5  2495.6
   673.3 2499.14     693 2504.03   732.3 2509.06   791.2 2527.38   830.4 2535.05
#Mann= 3 , 0 , 0
       0      .1       0   414.6    .045       0   429.6      .1       0
Bank Sta=414.6,429.6
XS Rating Curve= 0 ,0
Exp/Cntr=0.3,0.1

Type RM Length L Ch R = 1 ,7636.2  ,373.4,353,333.6
XS GIS Cut Line= 3
     1889490.368      153907.523     1889219.375      153581.079
     1888930.555      153255.667
#Sta/Elev= 30
       0 2541.84    29.6 2533.55    49.3 2532.18   128.3 2511.26   187.5 2502.37
   207.2 2495.99   236.8 2482.05     296 2448.38   325.6 2442.18   345.3 2429.03
   374.9 2416.78   416.8 2407.29   431.8  2406.5     444 2406.48   453.9 2406.62
   463.8 2410.15   483.6 2419.48   542.9 2441.02   572.6 2455.91   582.5 2455.18
   602.3 2447.38   612.2 2445.64   631.9 2449.23   720.9 2499.68   730.8 2503.74
   750.6 2508.03   770.4 2515.86   819.8 2540.28   839.6 2552.37   859.4 2559.55
#Mann= 3 , 0 , 0
       0      .1       0   416.8    .045       0   431.8      .1       0
Bank Sta=416.8,431.8
XS Rating Curve= 0 ,0
Exp/Cntr=0.3,0.1

Type RM Length L Ch R = 1 ,7283.6  ,435.2,447.4,461.2
XS GIS Cut Line= 3
     1889847.011      153321.798     1889340.866      153359.738
     1888989.101      153221.328
#Sta/Elev= 30
       0 2590.01    49.8 2584.54    89.6 2575.21   169.2 2531.83   179.1 2521.42
   248.8 2486.47   258.8 2476.28   328.4 2439.88   348.3 2425.62   390.6 2408.96
   405.6  2406.4     408 2406.26     428 2415.56   497.6 2422.55   527.5 2428.58
   587.2 2427.03     607 2433.31   636.9 2449.72   646.8 2453.49   656.8 2453.06
   676.7 2445.88   686.6 2445.16   696.6 2447.43   706.5 2452.97   726.4 2468.47
   756.3 2486.61   766.2 2499.54   776.2 2507.57   855.7 2546.99   885.6  2559.9
#Mann= 3 , 0 , 0
       0      .1       0   390.6    .045       0   405.6      .1       0
Bank Sta=390.6,405.6
XS Rating Curve= 0 ,0
Exp/Cntr=0.3,0.1