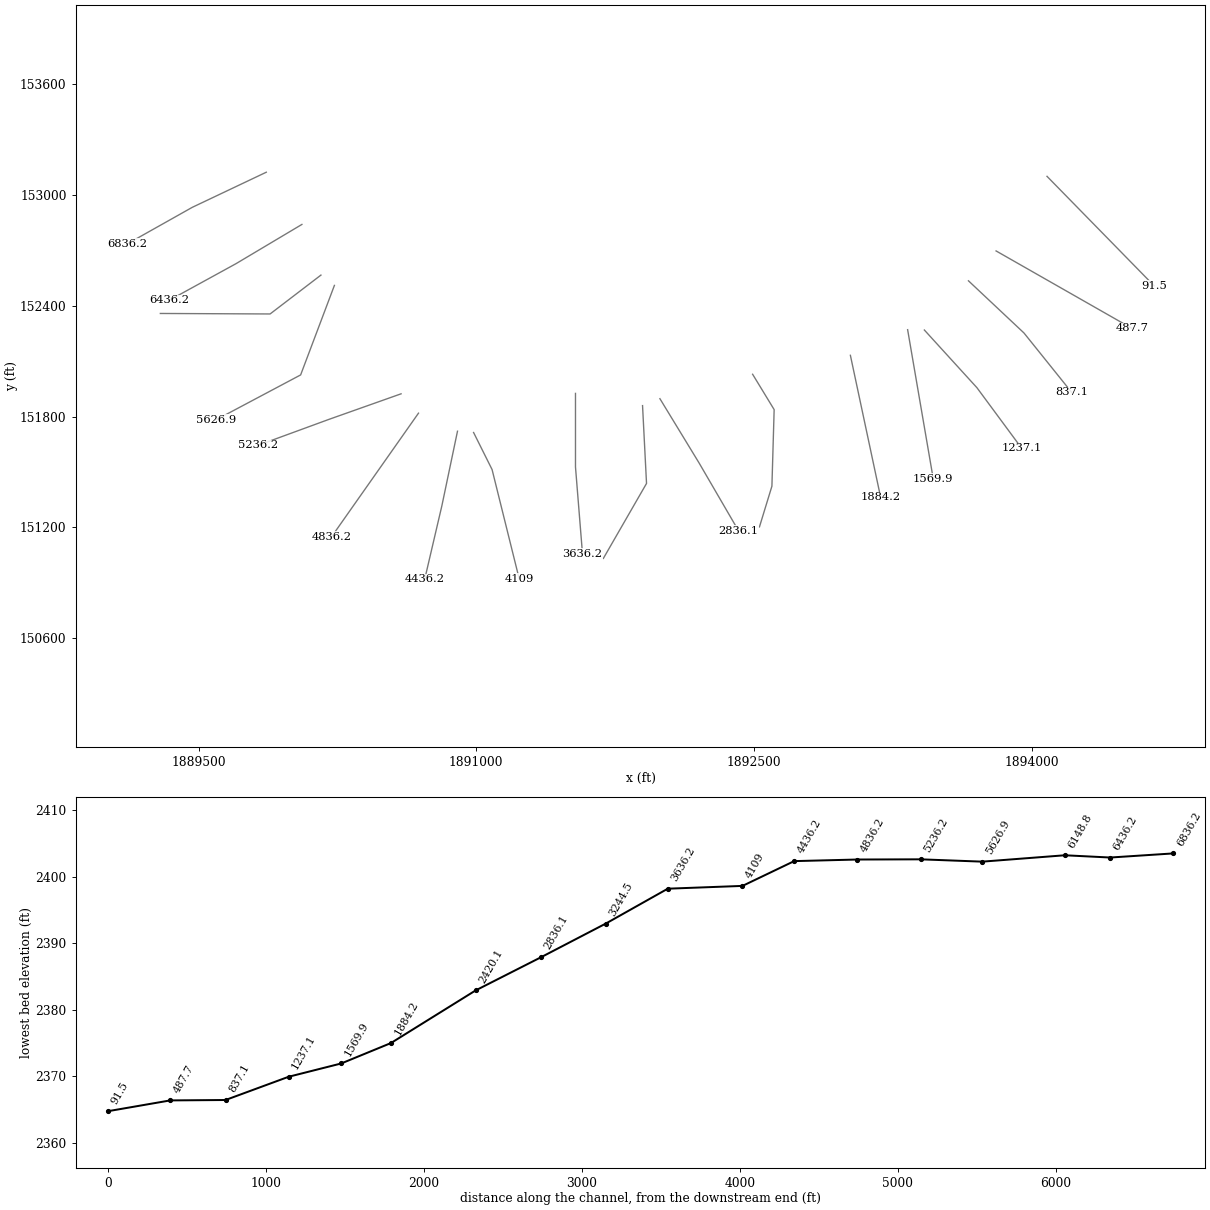
HEC-RAS study LfthndFrk.prj: LfthndFrk

--- LfthndFrk.g01 (geometry) --- (continued)

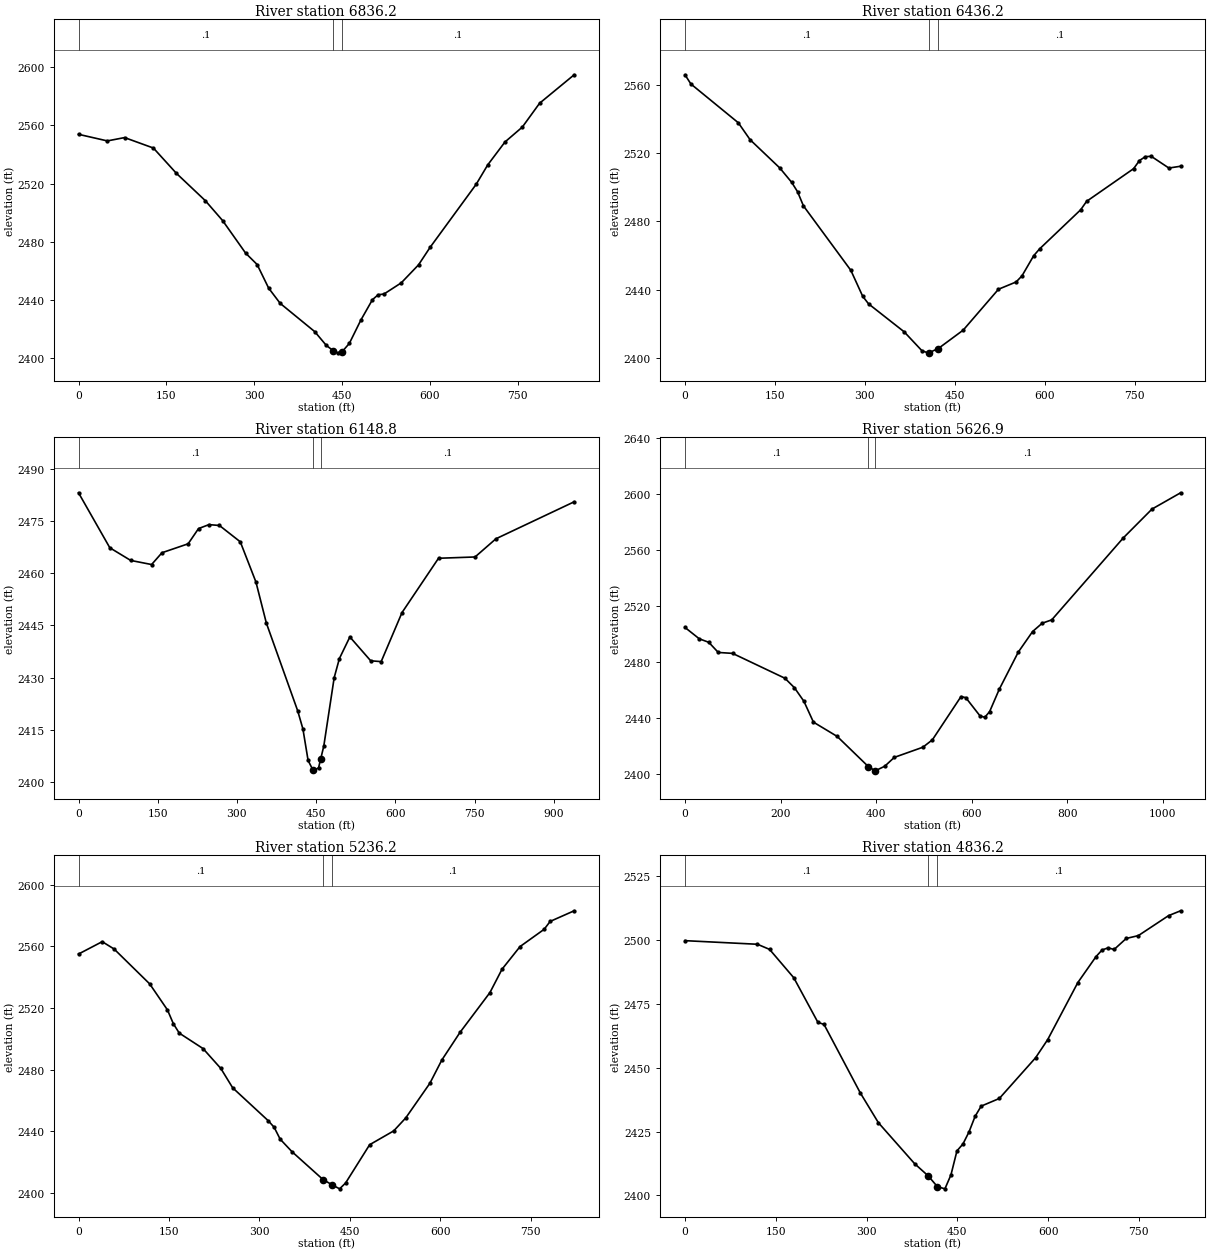
Type RM Length L Ch R = 1 ,6836.2  ,398,400,399.6
XS GIS Cut Line= 3
     1889866.122      153122.405      1889466.22      152932.272
     1889114.564      152734.156
#Sta/Elev= 30
       0 2553.89    49.2 2549.35    78.7 2551.64   127.9 2544.44   167.3 2526.98
   216.5 2508.25     246 2494.57   285.4 2472.12     305  2464.3   324.7 2448.03
   344.4 2437.55   403.4  2418.1   423.1 2408.65   435.3 2404.86   442.8 2403.51
   450.3 2404.37   462.5 2410.02   482.2  2426.1   501.9 2440.07   511.7 2443.49
   521.6 2443.98   551.1 2451.66   580.6 2464.04   600.3 2476.06   679.1 2519.51
   698.8 2532.85   728.3 2548.64   757.8 2558.84   787.4 2575.29   846.4 2594.86
#Mann= 3 , 0 , 0
       0      .1       0   435.3    .045       0   450.3      .1       0
Bank Sta=435.3,450.3
XS Rating Curve= 0 ,0
Exp/Cntr=0.3,0.1

Type RM Length L Ch R = 1 ,6436.2  ,299.7,287.3,275.7
XS GIS Cut Line= 3
     1890058.514      152839.802     1889702.321      152627.288
     1889341.666      152429.087
#Sta/Elev= 30
       0 2566.07     9.9 2560.65    88.9 2537.91   108.6 2527.95     158  2511.4
   177.8 2502.98   187.6 2497.49   197.5 2489.13   276.5 2451.31   296.3 2436.06
   306.1 2431.62   365.4 2415.23     395 2404.14   404.9 2402.89   407.3 2403.05
   422.3 2405.42   463.8 2416.21   522.6  2440.2     552 2444.48   561.8 2448.05
   581.3 2459.87   591.1 2463.86   659.7 2486.86   669.5 2491.78   747.9 2510.97
   757.7 2515.75   767.5 2518.02   777.3 2518.22   806.7 2511.34   826.3  2512.4
#Mann= 3 , 0 , 0
       0      .1       0   407.3    .045       0   422.3      .1       0
Bank Sta=407.3,422.3
XS Rating Curve= 0 ,0
Exp/Cntr=0.3,0.1

Type RM Length L Ch R = 1 ,6148.8  ,493.6,521.9,550.2
XS GIS Cut Line= 3
     1890161.266      152565.616     1889886.673      152355.229
     1889293.929      152357.911
#Sta/Elev= 30
       0 2483.06    59.3 2467.27    98.8 2463.64   138.4 2462.46   158.1 2465.85
   207.6 2468.41   227.3 2472.78   247.1 2473.92   266.9 2473.67   306.4 2468.98
     336 2457.45   355.8 2445.63   415.1 2420.46     425 2415.25   434.8 2406.22
   443.6 2403.56   444.7 2403.23   454.6 2404.09   458.6 2406.61   464.5 2410.32
   484.2 2429.98   494.1 2435.48   513.9 2441.67   553.4 2434.82   573.2 2434.59
   612.7 2448.68   681.8 2464.26     751 2464.63   790.5 2469.85   938.7 2480.47
#Mann= 3 , 0 , 0
       0      .1       0   443.6    .045       0   458.6      .1       0
Bank Sta=443.6,458.6
XS Rating Curve= 0 ,0
Exp/Cntr=0.3,0.1

Type RM Length L Ch R = 1 ,5626.9  ,411,390.7,370.6
XS GIS Cut Line= 3
     1890234.012      152509.837     1890051.622      152025.331
     1889592.983       151781.26
#Sta/Elev= 30
       0 2504.73    29.9 2496.62    49.8 2494.11    69.7 2486.86    99.6  2486.2
   209.1 2468.44     229 2461.68   248.9 2451.96   268.8 2437.07   318.6 2426.84
   383.6 2405.35   398.2 2402.27   398.6 2402.35   418.1 2405.58     438 2411.88
   497.8 2419.14   517.7 2424.42   577.6 2455.33   587.6 2454.57   617.6 2441.43
   627.6 2440.57   637.6 2444.66   657.6  2460.5   697.5 2487.13   727.5 2501.83
   747.5 2507.75   767.5 2510.15   917.3 2568.74   977.3 2589.31  1037.2 2600.95
#Mann= 3 , 0 , 0
       0      .1       0   383.6    .045       0   398.6      .1       0
Bank Sta=383.6,398.6
XS Rating Curve= 0 ,0
Exp/Cntr=0.3,0.1

Type RM Length L Ch R = 1 ,5236.2  ,386,400,413.7
XS GIS Cut Line= 3
     1890594.085       151923.04     1890204.951      151784.886
     1889821.078      151643.991
#Sta/Elev= 30
       0 2554.94    39.3 2562.97      59 2558.21     118 2535.58   147.5 2518.68
   157.3  2509.7   167.1 2503.63   206.5 2493.61     236  2480.7   255.6 2468.16
   314.6  2446.8   324.4 2442.54   334.3 2434.86   353.9 2426.74   405.4 2408.64
   420.4 2405.24   432.9 2402.62   442.8  2406.4   482.7 2431.24   522.6 2440.21
   542.6 2448.65   582.5 2471.06   602.4 2486.19   632.4 2504.05   682.2 2529.98
   702.2 2545.11   732.1  2559.8     772 2570.98     782 2576.11   821.8 2583.01
#Mann= 3 , 0 , 0
       0      .1       0   405.4    .045       0   420.4      .1       0
Bank Sta=405.4,420.4
XS Rating Curve= 0 ,0
Exp/Cntr=0.3,0.1

Type RM Length L Ch R = 1 ,4836.2  ,390.9,400,408.6
XS GIS Cut Line= 3
     1890688.119      151818.313     1890452.891      151483.114
     1890217.664      151147.915
#Sta/Elev= 30
       0 2499.68   119.8 2498.27   139.8 2496.26   179.8 2485.16   219.7  2467.7
   229.7 2466.93   289.6 2440.16   319.6 2428.46   379.5 2412.42     402 2407.64
     417 2403.46   429.5 2402.59   439.5 2408.06   449.4 2417.44   459.4 2420.17
   469.4  2424.9   479.4 2430.96   489.4 2434.94   519.4 2437.94   579.3 2453.86
   599.3 2460.96   649.2 2483.31   679.2 2493.44   689.2 2496.04   699.2 2496.87
   709.1 2496.23   729.1 2500.54   749.1 2501.65     799 2509.46     819 2511.37
#Mann= 3 , 0 , 0
       0      .1       0     402    .045       0     417      .1       0
Bank Sta=402,417
XS Rating Curve= 0 ,0
Exp/Cntr=0.3,0.1

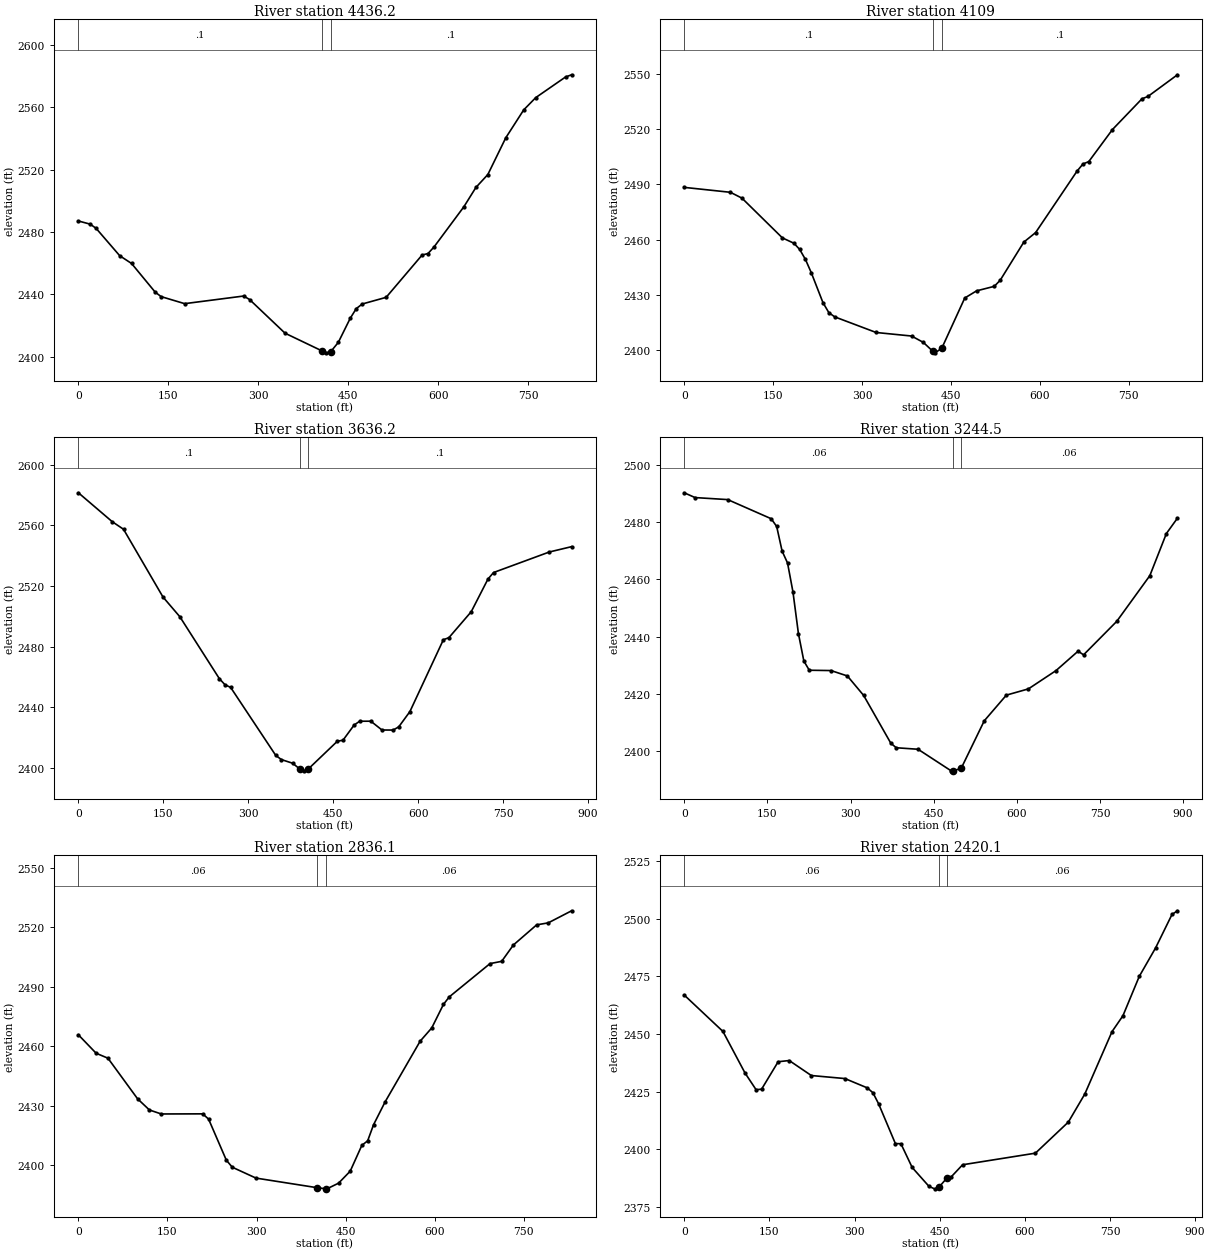
Type RM Length L Ch R = 1 ,4436.2  ,316.8,327,337.8
XS GIS Cut Line= 3
     1890898.788      151720.659     1890814.197       151316.17
     1890721.378      150918.091
#Sta/Elev= 30
       0 2486.99    19.7 2484.95    29.5 2482.27    68.9 2464.68    88.6 2459.72
   127.9 2441.36   137.8 2438.45   177.1 2433.92   275.5 2438.82   285.3 2436.57
   344.4 2414.96   405.7 2403.65   413.2 2402.35   420.7 2403.17   433.2 2409.07
   453.1 2424.56   463.1 2430.73   473.1  2433.7   512.9 2437.98   572.8 2465.12
   582.7 2466.11   592.7 2470.31   642.5 2496.14   662.5 2508.51   682.4 2516.81
   712.3 2540.39   742.2 2558.31   762.2 2566.17     812 2579.45     822 2580.84
#Mann= 3 , 0 , 0
       0      .1       0   405.7    .045       0   420.7      .1       0
Bank Sta=405.7,420.7
XS Rating Curve= 0 ,0
Exp/Cntr=0.3,0.1

Type RM Length L Ch R = 1 ,4109    ,478.8,472.8,468.7
XS GIS Cut Line= 3
     1890985.717      151713.585     1891085.571       151513.05
     1891231.745      150922.989
#Sta/Elev= 30
       0 2488.38    77.9 2485.71    97.4 2482.54   165.6 2460.98   185.1 2458.06
   194.8  2454.7   204.5 2449.27   214.3 2442.11     234 2425.87     244  2420.4
   253.9 2418.13   323.7 2409.66   383.5 2407.74   403.4 2404.27   419.5 2399.41
   423.3 2398.62   434.5 2401.16   473.2 2428.36   493.1 2432.24     523  2434.7
     533 2438.01   572.8 2458.69   592.7 2463.85   662.5 2497.16   672.5 2501.05
   682.4 2502.38   722.3 2519.75   772.1 2536.43   782.1 2537.69   831.9 2549.46
#Mann= 3 , 0 , 0
       0      .1       0   419.5    .045       0   434.5      .1       0
Bank Sta=419.5,434.5
XS Rating Curve= 0 ,0
Exp/Cntr=0.3,0.1

Type RM Length L Ch R = 1 ,3636.2  ,403.7,391.6,377.8
XS GIS Cut Line= 3
     1891536.055      151925.323     1891536.055      151526.981
     1891573.973      151055.776
#Sta/Elev= 30
       0 2581.54    59.8 2562.47    79.7 2557.49   149.4 2512.81   179.2  2499.8
     249 2458.96   258.9 2454.98   268.9 2453.21   348.6 2408.36   358.5 2405.63
   378.4 2403.21   390.8 2399.47   398.3  2398.2   405.8 2399.32   457.4 2417.73
   467.3 2418.38     487  2428.4   496.8 2430.91   516.5 2430.93   536.2 2425.12
   555.9 2425.09   565.8 2427.21   585.5 2437.26   644.6 2484.64   654.4 2486.01
   693.8  2503.1   723.3  2524.6   733.2 2528.95   831.7 2542.49   871.1 2546.02
#Mann= 3 , 0 , 0
       0      .1       0   390.8    .045       0   405.8      .1       0
Bank Sta=390.8,405.8
XS Rating Curve= 0 ,0
Exp/Cntr=0.3,0.1

Type RM Length L Ch R = 1 ,3244.5  ,380.8,408.4,433.9
XS GIS Cut Line= 3
     1891898.226      151859.173     1891919.703      151437.952
     1891686.558      151032.239
#Sta/Elev= 30
       0 2490.37    19.6 2488.69    78.5 2487.98   156.9 2481.28   166.8 2478.57
   176.6 2469.93   186.4 2465.77   196.2  2455.6     206 2441.07   215.8 2431.44
   225.6  2428.2   264.8 2428.09   294.3  2426.2   323.7 2419.37   372.7 2402.64
   382.5 2401.05   421.8 2400.52   481.5 2392.96   484.5 2392.97   499.5 2393.78
   541.2 2410.47   581.1 2419.48   620.9 2421.67   670.7 2428.08   710.5 2434.88
   720.4  2433.6   780.2 2445.32   839.9 2461.33   869.8  2476.1   889.7 2481.47
#Mann= 3 , 0 , 0
       0     .06       0   484.5    .045       0   499.5     .06       0
Bank Sta=484.5,499.5
XS Rating Curve= 0 ,0
Exp/Cntr=0.3,0.1

Type RM Length L Ch R = 1 ,2836.1  ,428.9,415.9,403.3
XS GIS Cut Line= 3
     1891992.018      151896.657     1892204.385      151547.413
     1892416.231      151182.515
#Sta/Elev= 30
       0 2465.73    29.9 2456.42    49.8 2453.92    99.7  2433.4   119.6 2427.76
   139.6 2425.74   209.4  2425.8   219.3 2423.14   249.2 2402.38   259.2 2398.83
   299.1 2393.34   401.2 2388.53   416.2 2387.96   418.6 2387.91   438.2 2390.77
   457.8 2396.83   477.4 2409.88   487.2 2412.18   497.1 2420.28   516.7 2431.91
   575.6 2462.51   595.2 2469.24   614.8 2481.08   624.6 2484.89   693.3 2501.72
   712.9 2502.86   732.6 2511.11   771.8 2521.29   791.4 2522.31   830.7 2528.41
#Mann= 3 , 0 , 0
       0     .06       0   401.2    .045       0   416.2     .06       0
Bank Sta=401.2,416.2
XS Rating Curve= 0 ,0
Exp/Cntr=0.3,0.1

Type RM Length L Ch R = 1 ,2420.1  ,530.4,535.9,541.3
XS GIS Cut Line= 4
     1892492.702      152028.879     1892609.019      151837.539
     1892596.933        151423.2     1892529.595      151202.784
#Sta/Elev= 30
       0 2466.95    68.2 2451.16   107.1 2433.14   126.6 2425.89   136.3 2426.11
   165.5 2438.02     185 2438.54   223.9 2432.04   283.1 2430.72   322.6 2426.67
   332.5 2424.56   342.4  2419.8     372 2402.53   381.8 2402.45   401.6 2392.16
   431.2 2383.97     441 2382.89   448.5 2383.53   463.5 2387.78   470.7 2388.17
   490.4 2393.33   618.7 2398.36   676.8 2411.87   705.7    2424   753.7 2451.09
   772.9 2457.96   801.7 2475.05   830.5 2487.42   859.3 2501.88   868.9 2503.49
#Mann= 3 , 0 , 0
       0     .06       0   448.5    .045       0   463.5     .06       0
Bank Sta=448.5,463.5
XS Rating Curve= 0 ,0
Exp/Cntr=0.3,0.1

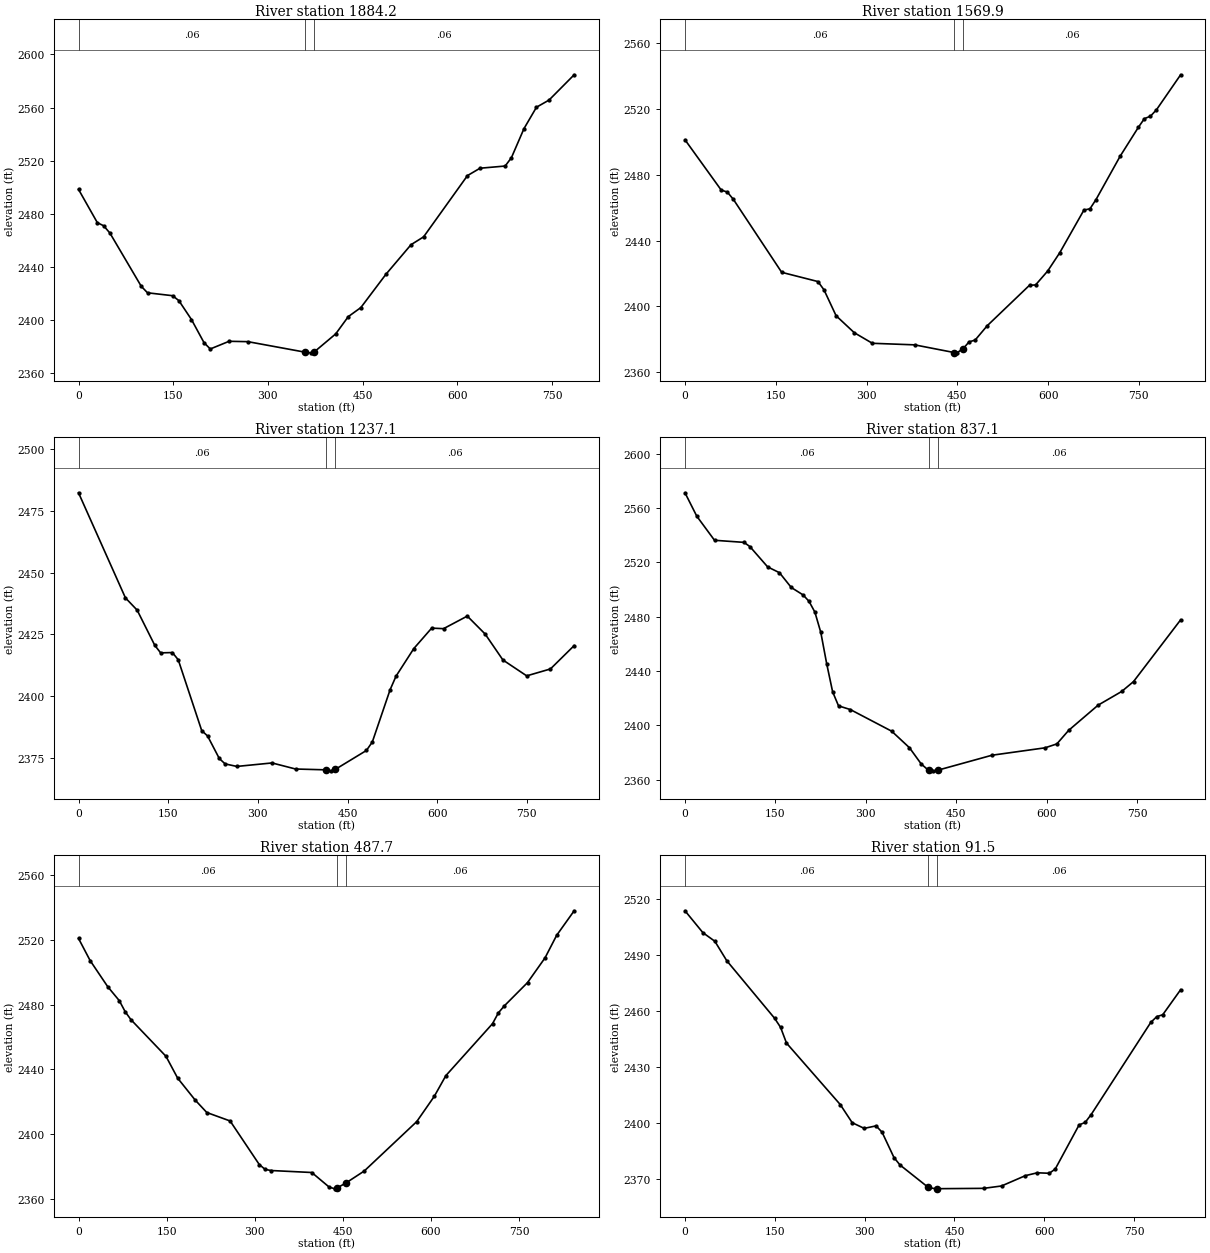
Type RM Length L Ch R = 1 ,1884.2  ,315.2,314.3,313.4
XS GIS Cut Line= 2
     1893020.704      152131.497     1893183.981      151363.607
#Sta/Elev= 30
       0 2498.26    29.8 2473.18    39.8 2470.81    49.7 2465.34    99.4 2425.15
   109.3 2420.26   149.1 2418.06     159 2414.32   178.9  2400.1   198.8 2382.64
   208.7 2377.88   238.5 2383.68   268.3  2383.4   358.4 2375.51   367.7 2374.97
   373.4 2375.66   407.4 2389.27   427.3 2402.28   447.2 2409.11   486.9  2434.2
   526.7 2456.54   546.6 2462.45   616.1 2508.66     636 2514.22   675.8 2515.87
   685.7 2522.15   705.6 2544.08   725.4 2560.23   745.3 2565.62   785.1  2584.7
#Mann= 3 , 0 , 0
       0     .06       0   358.4    .045       0   373.4     .06       0
Bank Sta=358.4,373.4
XS Rating Curve= 0 ,0
Exp/Cntr=0.3,0.1

Type RM Length L Ch R = 1 ,1569.9  ,319.9,332.7,343.2
XS GIS Cut Line= 3
     1893329.877      152270.237     1893399.067      151866.625
     1893468.257      151463.012
#Sta/Elev= 30
       0 2501.08    59.9 2470.57    69.9  2469.4    79.9 2464.98   159.8 2420.72
   219.7 2415.12   229.7  2410.1   249.7 2394.39   279.7 2384.12   309.6 2377.69
   379.5 2376.74   444.9 2372.07   449.4  2371.9   459.9 2374.52   469.4 2378.56
   479.4 2379.62   499.4 2388.33   569.3 2412.88   579.3 2413.06   599.3  2421.5
   619.2 2432.56   659.2 2458.46   669.2 2459.24   679.2 2464.85   719.1 2491.15
   749.1  2508.6   759.1 2513.89   769.1 2515.37     779 2519.23     819 2540.49
#Mann= 3 , 0 , 0
       0     .06       0   444.9    .045       0   459.9     .06       0
Bank Sta=444.9,459.9
XS Rating Curve= 0 ,0
Exp/Cntr=0.3,0.1

Type RM Length L Ch R = 1 ,1237.1  ,397.5,399.7,401.2
XS GIS Cut Line= 3
     1893420.294      152268.316     1893704.188      151956.165
     1893945.882      151628.322
#Sta/Elev= 30
       0 2482.26    78.5 2439.79    98.1 2434.84   127.6 2420.61   137.4 2417.57
     157  2417.7   166.8  2414.8   206.1 2386.17   215.9 2383.99   235.5 2374.89
   245.3  2372.7   264.9 2371.68   323.8 2373.09   363.1 2370.64   414.4  2370.3
   421.9  2369.9   429.4 2370.46   481.6 2378.12   491.5 2381.54   521.3 2402.69
   531.2 2408.16     561 2419.33   590.8 2427.57   610.7 2427.35   650.4 2432.43
   680.2  2425.2     710  2414.7   749.8 2408.28   789.5 2411.07   829.2 2420.51
#Mann= 3 , 0 , 0
       0     .06       0   414.4    .045       0   429.4     .06       0
Bank Sta=414.4,429.4
XS Rating Curve= 0 ,0
Exp/Cntr=0.3,0.1

Type RM Length L Ch R = 1 ,837.1   ,345.1,349.5,354.8
XS GIS Cut Line= 3
     1893658.431      152534.638     1893958.136      152252.419
     1894215.113      151931.832
#Sta/Elev= 30
       0 2571.29    19.6 2554.03      49 2536.29      98 2534.75   107.8 2531.61
   137.2 2516.67   156.8 2512.39   176.4  2501.5     196 2496.02   205.8 2491.33
   215.6 2483.33   225.4 2468.38   235.2 2445.23     245 2424.65   254.8 2414.28
   274.4 2411.56   343.1 2395.59   372.5 2383.44   392.1 2371.42   404.2 2366.78
   411.7  2366.4   419.2 2366.83   509.5 2377.91   597.5 2383.36   617.1 2386.24
   636.7 2396.24   685.6 2414.81   724.7 2424.89   744.3 2432.16   822.5 2477.66
#Mann= 3 , 0 , 0
       0     .06       0   404.2    .045       0   419.2     .06       0
Bank Sta=404.2,419.2
XS Rating Curve= 0 ,0
Exp/Cntr=0.3,0.1

Type RM Length L Ch R = 1 ,487.7   ,402.1,395.6,389.1
XS GIS Cut Line= 2
     1893807.653      152696.326     1894540.345      152277.779
#Sta/Elev= 30
       0 2520.84    19.8 2507.17    49.6 2491.14    69.5 2482.41    79.4 2475.66
    89.3  2470.7   148.9 2448.11   168.8 2434.63   198.5 2421.16   218.4 2413.43
   258.1 2408.21   307.7 2381.35   317.7 2378.34   327.6 2377.65   397.1 2376.42
   426.9 2367.37   436.8 2366.34   439.7 2366.82   454.7 2369.82   486.4 2377.33
   575.8 2407.83   605.6 2423.38   625.4  2436.2   704.8 2468.24   714.8 2474.92
   724.7 2479.15   764.4  2493.6   794.2 2508.85     814 2522.76   843.8  2537.9
#Mann= 3 , 0 , 0
       0     .06       0   439.7    .045       0   454.7     .06       0
Bank Sta=439.7,454.7
XS Rating Curve= 0 ,0
Exp/Cntr=0.3,0.1

Type RM Length L Ch R = 1 ,91.5    ,86.3,91.8,97.3
XS GIS Cut Line= 2
     1894082.676      153100.082     1894660.895      152507.921
#Sta/Elev= 30
       0 2513.71    29.9 2501.99    49.9 2497.36    69.8 2486.94   149.6 2456.12
   159.6 2451.26   169.5 2442.82   259.3 2409.86   279.2 2400.16   299.2 2397.11
   319.1 2398.45   329.1 2395.04     349 2381.46     359  2377.5   406.3 2365.46
   418.8 2364.71   421.3 2364.79   498.6 2364.97   528.5 2366.24   568.4 2371.78
   588.3 2373.31   608.3 2373.05   618.2 2375.31   658.1 2398.98   668.1 2400.27
   678.1 2404.46   777.8 2453.92   787.8 2456.99   797.7    2458   827.6 2471.41
#Mann= 3 , 0 , 0
       0     .06       0   406.3    .045       0   421.3     .06       0
Bank Sta=406.3,421.3
XS Rating Curve= 0 ,0
Exp/Cntr=0.3,0.1

Chan Stop Cuts=-1
Use User Specified Reach Order=0
Composite Channel Slope=5